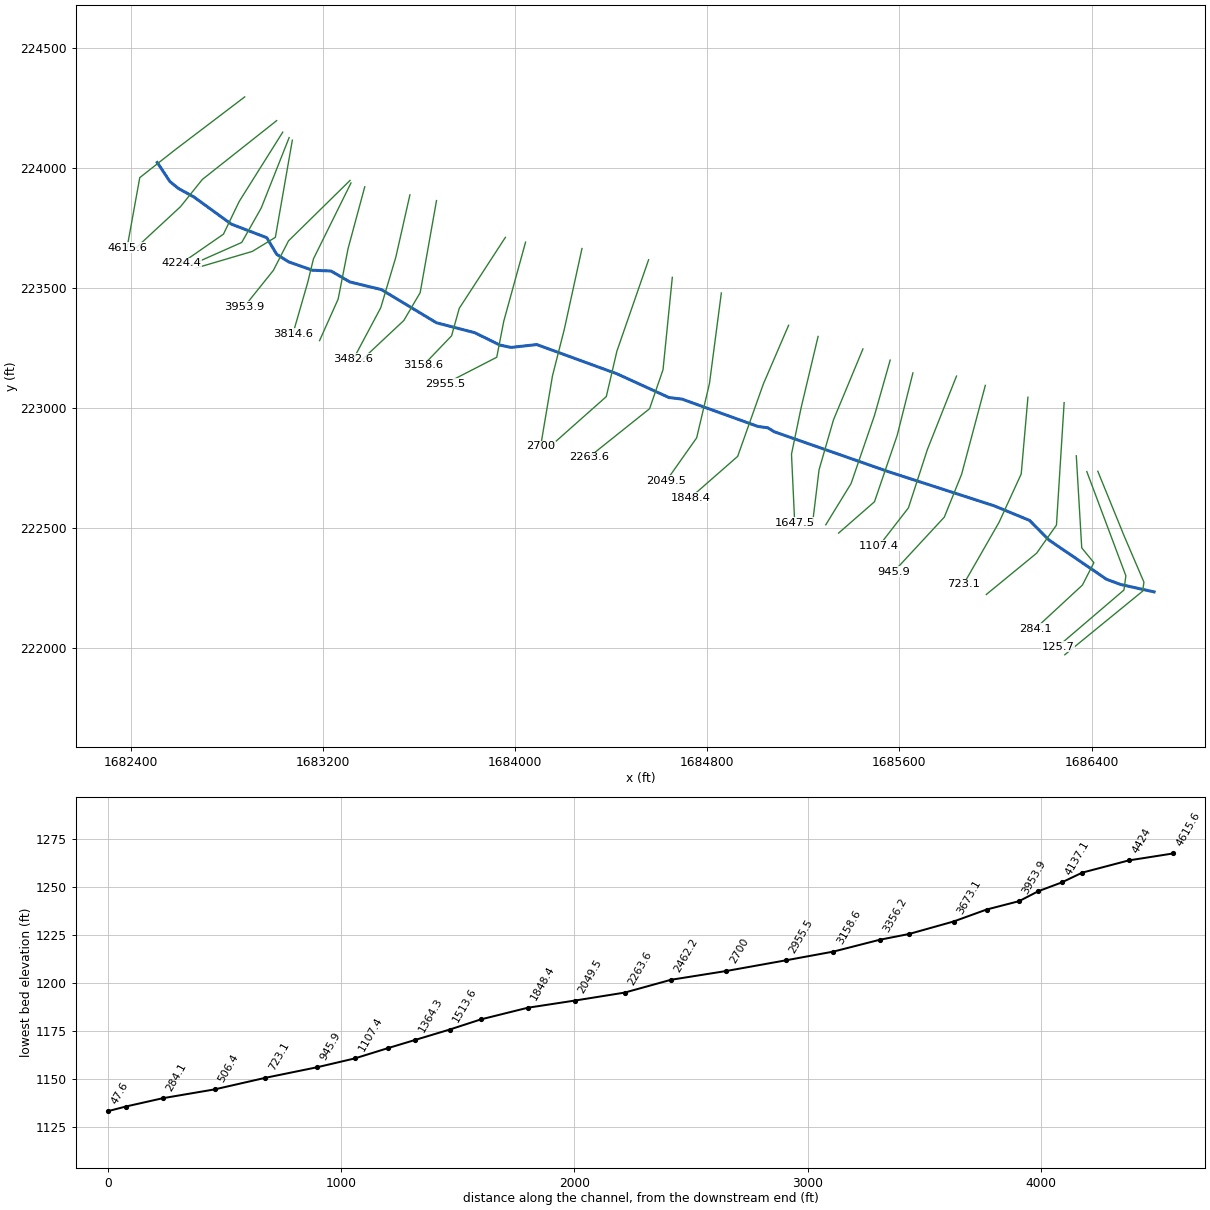
--- lfthndlftf.prj (project) ---

Proj Title=lfthndlftf
Current Plan=p01
Default Exp/Contr=0,0
English Units
Geom File=g01
Flow File=f01
Plan File=p01
BEGIN DESCRIPTION:
END DESCRIPTION:
DSS Export Rating Curves= 0
DSS Export Rating Curve Sorted= 0
DSS Export Volume Flow Curves= 0
DXF OffsetX= 0
DXF OffsetY= 0
DXF ScaleX= 0
DXF ScaleY= 0

--- lfthndlftf.p01 (plan) ---

Plan Title=Floodplain
Program Version=4.00
Geom File=g01
Flow File=f01
K Sum by GR=0
Std Step Tol=0.01
Critical Tol=0.01
Num of Std Step Trials=20
Max Error Tol=0.3
Flow Tol Ratio=0.001
Split Flow NTrial=30
Split Flow Tol=0.02
Split Flow Ratio=0.02
Log Output Level=0
Friction Slope Method=1
Unsteady Friction Slope Method=2
Unsteady Bridges Friction Slope Method=1
Global Log Level=0
CheckData=False
Run HTab=0
Run UNet=0
Run PostProcess=0
UNET Theta=0
UNET Theta Warmup=0
UNET ZTol=0
UNET ZSATol=0
UNET MxIter=0
UNET MaxInSteps=0
UNET DtIC=0
UNET DtMin=0
UNET MaxCRTS=0
UNET WFStab=0
UNET SFStab=0
UNET WFX=0
UNET SFX=0
UNET DSS MLevel=0
UNET DZMax Abort=0
UNET Convert EG Bridges=0
UNET Use Existing IB Tables=0
UNET Froude Limit=0
UNET Froude Power=0
Write IC File=0
Echo Input=False
Echo Output=False
Write Detailed=0

--- lfthndlftf.f01 (steady flow) ---

Flow Title=NFF Regression Equation
Program Version=4.00
Number of Profiles= 1
Profile Names=P100yr
River Rch & RM=lfthndlftf,Main            ,4615.6
     402
River Rch & RM=lfthndlftf,Main            ,3814.6
     417
River Rch & RM=lfthndlftf,Main            ,2955.5
     457
River Rch & RM=lfthndlftf,Main            ,284.1
     505
Boundary for River Rch & Prof#=lfthndlftf,Main            , 1
Up Type= 0
Dn Type= 3
Dn Slope=0.02
DSS Import GetInterval= 0
DSS Import GetPeak= 0
DSS Import FillOption= 0

--- lfthndlftf.g01 (geometry) ---

Geom Title=USGS 10m DEM
Program Version=4.00

River Reach=lfthndlftf      ,Main
Reach XY= 30
     1682510.461      224023.812     1682562.796      223944.873
     1682597.651      223916.238     1682663.117      223880.073
      1682818.53      223767.011     1682966.196      223710.306
     1683007.783       223640.82     1683057.792      223609.235
     1683156.757      223574.492     1683233.614      223571.333
     1683312.693      223525.564     1683443.711      223493.746
      1683672.76      223355.342     1683832.388      223313.909
     1683936.498      223262.443     1683983.062      223252.487
      1684090.38      223264.463     1684424.704      223142.263
     1684640.838      223043.404     1684694.573      223037.089
      1685010.68      222923.019      1685052.43      222917.265
     1685077.747      222901.193     1685557.017      222733.329
     1685994.211      222591.875     1686141.419      222531.163
     1686222.631      222449.063     1686462.346      222285.256
      1686520.98      222263.579     1686660.137      222232.694

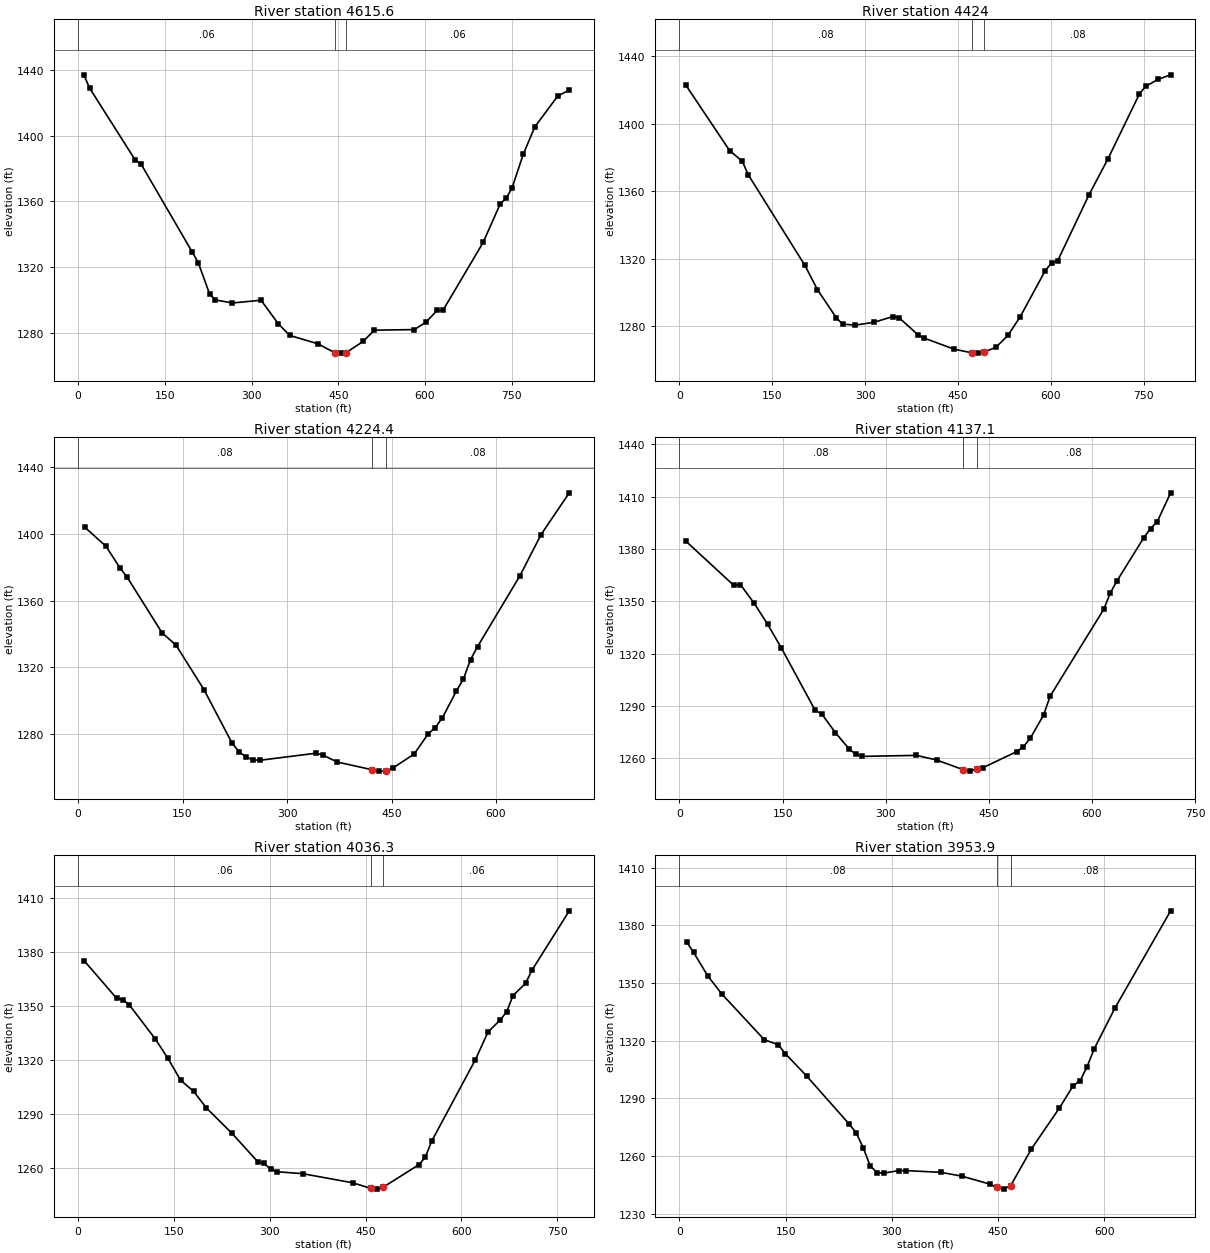
Type RM Length L Ch R = 1 ,4615.6  ,185.9,191.6,197.4
XS GIS Cut Line= 4
     1682874.361      224297.513     1682583.267      224075.847
     1682437.579       223960.83     1682384.536      223667.714
#Sta/Elev= 30
     9.9 1436.99    19.8 1428.98    98.9 1385.11   108.8 1382.75   197.8 1328.95
   207.7 1322.84   227.4 1303.69   237.3 1300.08     267 1298.25   316.4  1299.9
   346.1 1285.66   365.9 1278.52   414.7 1273.42   443.8 1267.99   453.8 1267.74
   463.8  1268.1   492.9 1274.85   512.4 1281.72   581.3 1282.05   601.1 1286.44
     621  1293.7   630.9 1293.71   700.4 1335.02   730.2 1358.66   740.2 1361.92
   750.1  1367.9   769.9 1388.72   789.8 1405.33   829.5  1424.1   849.4 1427.73
#Mann= 3 , 0 , 0
       0     .06       0   443.8    .045       0   463.8     .06       0
Bank Sta=443.8,463.8
XS Rating Curve= 0 ,0
Exp/Cntr=0.3,0.1

Type RM Length L Ch R = 1 ,4424    ,193.8,199.5,205.3
XS GIS Cut Line= 4
     1683007.405      224198.554     1682697.971      223953.141
     1682607.275       223839.77     1682421.881      223667.714
#Sta/Elev= 30
    10.1 1423.12      81  1384.2   101.3 1377.93   111.4 1369.69   202.5 1316.14
   222.8 1301.73   253.2 1285.08   263.3 1281.29   283.5  1280.7   313.9 1282.33
   344.3 1285.75   354.4 1285.14   384.8 1275.07   394.9 1273.01   443.3 1266.45
     472 1264.27   482.1 1264.08     492 1264.76   511.1 1267.55   530.4 1274.59
   550.2 1285.63   590.7 1313.03   600.8 1317.49   610.9 1318.98   661.5 1358.11
   691.9 1379.28   742.5 1417.61   752.6 1422.22   772.8 1426.44   793.1 1429.12
#Mann= 3 , 0 , 0
       0     .08       0     472    .045       0     492     .08       0
Bank Sta=472,492
XS Rating Curve= 0 ,0
Exp/Cntr=0.3,0.1

Type RM Length L Ch R = 1 ,4224.4  ,89.1,87.4,85.6
XS GIS Cut Line= 4
     1683032.747      224150.539     1682851.354      223861.111
        1682786.      223725.066     1682611.276      223603.693
#Sta/Elev= 30
      10 1403.96    40.2 1392.61    60.3 1379.57    70.3 1374.18   120.6 1340.69
   140.6 1333.35   180.8 1306.53     221 1274.55   231.1 1269.36   241.1 1266.19
   251.2 1264.42   261.2 1264.22   341.6 1268.46   351.6 1267.34   371.8 1263.19
   422.1 1258.53   432.1  1257.7   442.1 1257.71   452.3 1259.69   482.4 1267.91
   502.6 1280.06   512.8 1283.87   522.9 1289.65   543.2 1305.87   553.3 1313.07
   563.4 1324.65   573.5 1332.45   634.3 1374.93   664.7 1399.73   705.2 1424.77
#Mann= 3 , 0 , 0
       0     .08       0   422.1    .045       0   442.1     .08       0
Bank Sta=422.1,442.1
XS Rating Curve= 0 ,0
Exp/Cntr=0.3,0.1

Type RM Length L Ch R = 1 ,4137.1  ,113.8,100.7,87.7
XS GIS Cut Line= 4
     1683059.422      224127.864     1682943.385      223834.435
     1682862.025      223690.388     1682648.622      223595.691
#Sta/Elev= 30
     9.9 1384.26    78.9 1359.14    88.7 1359.52   108.5 1348.96   128.2 1336.82
   147.9 1323.44   197.2 1287.61   207.1  1285.3   226.8 1274.69   246.5 1265.45
   256.4 1262.26   266.2 1261.06   344.7 1261.64   373.9    1259   412.6 1253.47
   422.6 1252.61   432.6 1253.93     442 1254.68   490.7 1263.83   500.4 1266.64
   510.2 1271.39   529.6 1284.77   539.3 1295.69   617.2 1345.44   626.9 1354.94
   636.6  1361.8   675.5 1386.53   685.3  1391.7     695 1395.68   714.4 1412.16
#Mann= 3 , 0 , 0
       0     .08       0   412.6    .045       0   432.6     .08       0
Bank Sta=412.6,432.6
XS Rating Curve= 0 ,0
Exp/Cntr=0.3,0.1

Type RM Length L Ch R = 1 ,4036.3  ,68.5,82.4,96.4
XS GIS Cut Line= 4
      1683072.76      224117.194      1683002.07      223711.729
     1682906.039      223653.043     1682671.296      223583.687
#Sta/Elev= 30
      10  1374.8    60.2 1354.16    70.3  1353.3    80.3 1350.38   120.5 1331.66
   140.5 1320.77   160.6 1308.51   180.7 1302.43   200.8 1293.18   240.9 1279.04
   281.1  1263.3   291.1 1262.29   301.2 1259.16   311.2 1257.68   351.4 1256.61
   430.3  1251.5   457.9 1248.46   467.9 1248.01   477.9 1249.15   533.9 1261.68
   543.7 1265.91   553.5 1274.66     622 1320.03   641.6  1335.3   661.2 1342.22
     671 1346.69   680.8 1355.61   700.4 1362.39   710.2 1369.58   768.9 1402.75
#Mann= 3 , 0 , 0
       0     .06       0   457.9    .045       0   477.9     .06       0
Bank Sta=457.9,477.9
XS Rating Curve= 0 ,0
Exp/Cntr=0.3,0.1

Type RM Length L Ch R = 1 ,3953.9  ,133.4,139.3,145.1
XS GIS Cut Line= 4
     1683312.838      223949.139     1683056.755      223697.057
     1682994.068       223574.35     1682871.361      223420.967
#Sta/Elev= 30
      10 1371.39      20 1365.85    39.9 1353.71    59.9 1344.23   119.8 1320.51
   139.7 1317.85   149.7 1313.16   179.7 1301.59   239.6 1276.67   249.5 1272.14
   259.5 1264.36   269.5 1254.78   279.5 1251.32   289.5 1251.22   309.4 1252.43
   319.4 1252.46   369.2 1251.56   398.7 1249.57   438.1 1245.46   447.8  1243.8
   457.8 1242.83   467.8  1244.7   497.1 1263.76   536.4 1284.92   556.1 1296.65
   565.9  1299.2   575.7 1306.53   585.5 1315.61     615 1336.98   693.6 1387.49
#Mann= 3 , 0 , 0
       0     .08       0   447.8    .045       0   467.8     .08       0
Bank Sta=447.8,467.8
XS Rating Curve= 0 ,0
Exp/Cntr=0.3,0.1

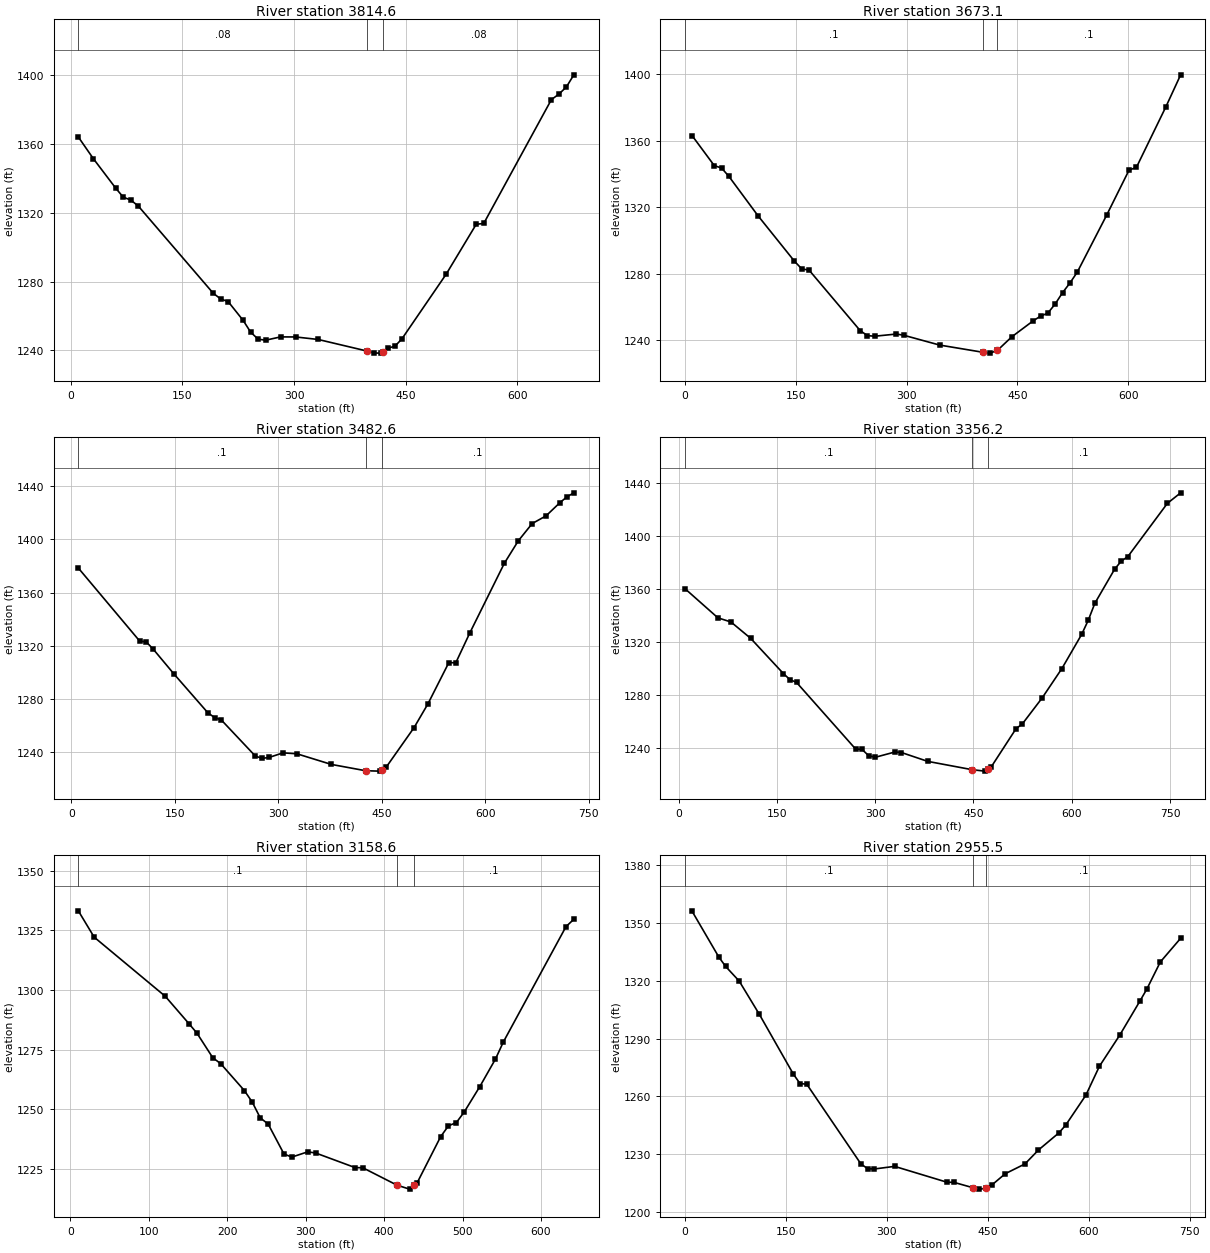
Type RM Length L Ch R = 1 ,3814.6  ,139.2,141.5,143.2
XS GIS Cut Line= 4
      1683316.84      223938.469     1683160.789      223622.366
     1683136.781      223523.667     1683075.428      223310.264
#Sta/Elev= 30
    10.1 1364.16    30.2 1351.61    60.4 1334.37    70.5 1329.17    80.6 1327.47
    90.6 1324.05   191.4 1273.29   201.4 1269.96   211.5 1268.42   231.7 1257.45
   241.7 1250.66   251.8 1246.55   261.9 1245.98     282 1247.89   302.2 1247.85
   332.4  1246.4   398.7  1239.6   407.9 1238.51   417.2 1238.45  420.15 1239.36
   426.4 1241.35   435.6 1242.47   444.9 1246.67   504.6 1284.43   544.9  1313.4
     555 1313.86   645.9 1385.88     656 1389.08   666.1 1393.27   676.1 1400.31
#Mann= 3 , 0 , 0
    10.1     .08       0   398.7    .045       0  420.15     .08       0
Bank Sta=398.7,420.15
XS Rating Curve= 0 ,0
Exp/Cntr=0.3,0.1

Type RM Length L Ch R = 1 ,3673.1  ,193.9,190.6,187.8
XS GIS Cut Line= 4
     1683374.192      223922.464     1683304.836      223665.047
     1683263.489      223454.311      1683186.13      223280.921
#Sta/Elev= 30
     9.9 1362.69    39.5 1344.94    49.4 1343.46    59.2 1338.52    98.7  1314.8
   148.1 1287.47     158 1282.84   167.9 1282.12     237 1245.81   246.8 1242.74
   256.7 1242.37   286.1 1243.68   295.9 1242.99   344.7 1237.06     403 1232.75
     413 1232.21     423 1233.84   442.3 1241.95   471.6 1251.67   481.4 1254.43
   491.3 1256.25   501.3 1261.77   511.3  1268.6   521.3 1274.38   531.3 1280.99
   571.3 1315.43   601.3 1342.22   611.3 1343.88   651.2 1380.28   671.2 1399.51
#Mann= 3 , 0 , 0
       0      .1       0     403    .045       0     423      .1       0
Bank Sta=403,423
XS Rating Curve= 0 ,0
Exp/Cntr=0.3,0.1

Type RM Length L Ch R = 1 ,3482.6  ,132.6,126.3,120.1
XS GIS Cut Line= 4
     1683562.253       223889.12     1683503.567      223629.035
      1683440.88        223418.3      1683327.51      223204.896
#Sta/Elev= 30
     9.9 1378.46    98.7 1323.61   108.6 1322.75   118.5 1317.42   148.1 1299.03
   197.5 1269.68   207.4 1265.97   217.2 1264.16   266.6 1236.97   276.6  1235.3
   286.6 1236.03   306.6 1239.44   326.6 1238.76   376.6 1230.75   426.5 1225.98
   446.5  1225.7  450.05 1226.81   456.5 1228.95   496.6  1258.5   516.7 1276.37
   546.9 1307.32     557 1307.18   577.1  1329.4   627.4 1382.06   647.6 1398.92
   667.7 1411.89   687.9 1417.73     708 1427.66   718.1 1431.99   728.1 1435.02
#Mann= 3 , 0 , 0
     9.9      .1       0   426.5    .045       0  450.05      .1       0
Bank Sta=426.5,450.05
XS Rating Curve= 0 ,0
Exp/Cntr=0.3,0.1

Type RM Length L Ch R = 1 ,3356.2  ,191.1,197.7,204.2
XS GIS Cut Line= 4
     1683672.956      223865.112     1683604.934      223480.987
     1683536.912      223364.949     1683360.854      223199.562
#Sta/Elev= 30
      10 1360.17      60 1338.28      80 1335.13     110 1322.82     160 1296.22
     170 1291.67     180 1289.58   270.1 1239.37   280.1 1238.98   290.1 1234.33
   300.1 1233.11   330.1 1237.09   340.1 1236.71   380.1 1230.04   447.7 1223.78
     467 1222.67  471.96    1224   476.6 1225.44     515 1254.67   524.6 1258.25
   554.8 1277.83     585 1300.04   615.2 1325.82   625.3 1336.56   635.3 1349.27
   665.5 1374.99   675.6 1381.05   685.6 1384.43     746 1424.63   766.2 1432.54
#Mann= 3 , 0 , 0
      10      .1       0   447.7    .045       0  471.96      .1       0
Bank Sta=447.7,471.96
XS Rating Curve= 0 ,0
Exp/Cntr=0.3,0.1

Type RM Length L Ch R = 1 ,3158.6  ,200.6,203.1,205.4
XS GIS Cut Line= 4
     1683959.716      223711.729     1683767.653      223415.632
     1683735.643      223300.928     1683618.271      223178.221
#Sta/Elev= 30
    10.1 1333.16    30.3 1322.13     121 1297.32   151.3  1285.8   161.3 1281.91
   181.5  1271.6   191.6  1269.1   221.8 1257.83   231.9 1252.95     242  1246.4
   252.1  1243.8   272.3 1231.23   282.3 1229.95   302.5 1232.14   312.6 1231.67
   362.9 1225.55   372.8 1225.47   416.2 1218.21   432.3 1216.52  437.99 1218.11
   442.2 1219.26     472  1238.5     482 1243.07     492  1244.4     502 1248.82
     522 1259.53   541.9 1271.05   551.9 1278.17   631.8 1326.54   641.8 1329.62
#Mann= 3 , 0 , 0
    10.1      .1       0   416.2    .045       0  437.99      .1       0
Bank Sta=416.2,437.99
XS Rating Curve= 0 ,0
Exp/Cntr=0.3,0.1

Type RM Length L Ch R = 1 ,2955.5  ,257.2,255.5,254
XS GIS Cut Line= 4
     1684043.743      223691.722     1683953.047      223362.281
     1683923.704      223211.565     1683708.968      223100.863
#Sta/Elev= 30
      10 1356.15    50.2 1332.16    60.3 1327.32    80.4 1319.77   110.5 1302.45
   160.8 1271.64   170.8 1266.68   180.9 1266.32   261.3 1225.08   271.3 1222.58
   281.4 1222.42   311.5 1223.77   389.7 1215.52   399.3 1215.53   427.7 1212.74
   437.7 1211.98   447.7 1212.39   456.9 1214.35     476 1219.96   505.3 1225.03
   525.4 1232.25   555.6 1241.07   565.7 1245.04   595.9 1260.65     616 1275.61
   646.2 1291.72   676.4  1309.5   686.5 1315.58   706.6 1329.66   736.8 1341.92
#Mann= 3 , 0 , 0
       0      .1       0   427.7    .045       0   447.7      .1       0
Bank Sta=427.7,447.7
XS Rating Curve= 0 ,0
Exp/Cntr=0.3,0.1

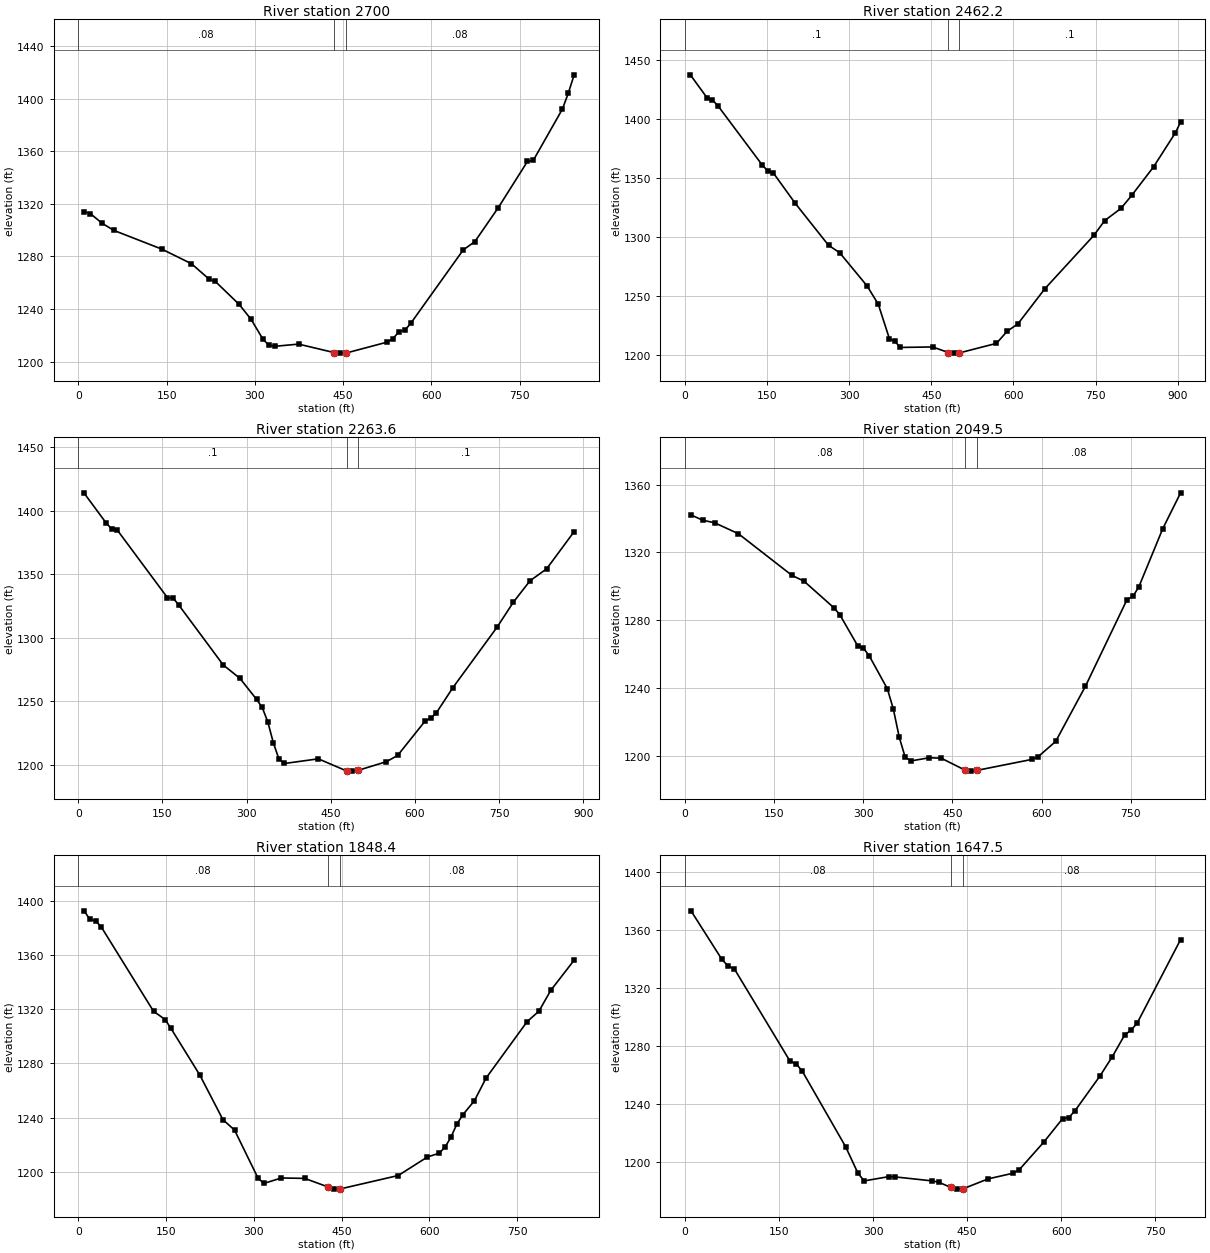
Type RM Length L Ch R = 1 ,2700    ,237.3,237.7,238.2
XS GIS Cut Line= 4
     1684278.487      223665.047     1684205.129      223328.937
      1684155.78      223134.207     1684106.431      222840.778
#Sta/Elev= 30
    10.1    1314    20.2 1312.59    40.5 1305.12    60.7 1299.67   141.7 1285.53
   192.2  1274.4   222.6 1262.53   232.7 1260.95   273.2 1243.49   293.4 1232.18
   313.7 1216.98   323.8 1212.45   333.9 1211.58   374.2 1213.26   434.5 1206.83
   444.5  1206.4   454.5 1206.42   524.8 1214.77   534.9 1217.46   544.9 1222.84
   554.8 1223.82   564.7 1228.97     654 1284.88   673.8 1291.23   713.5    1317
   763.1 1352.17     773 1352.95   822.6 1392.06   832.5 1404.08   842.5 1418.06
#Mann= 3 , 0 , 0
       0     .08       0   434.5    .045       0   454.5     .08       0
Bank Sta=434.5,454.5
XS Rating Curve= 0 ,0
Exp/Cntr=0.3,0.1

Type RM Length L Ch R = 1 ,2462.2  ,201.2,198.6,196
XS GIS Cut Line= 4
     1684555.911      223618.365     1684423.868      223236.907
     1684379.853      223047.512     1684150.445      222843.445
#Sta/Elev= 30
    10.1 1437.65    40.4 1418.34    50.5 1416.33    60.5 1411.41   141.3 1361.25
   151.4 1356.29   161.5 1354.58   201.8 1328.63   262.4 1293.19   282.6 1286.95
     333 1258.61   353.2 1243.22   373.4 1214.19   383.5 1211.71   393.6 1206.64
   452.3 1207.04   481.2 1202.33   491.2 1201.81   501.2 1202.01   568.9 1210.07
   588.4 1220.31     608 1226.58   657.5 1256.49   746.7 1301.58   766.5 1314.13
   796.2 1324.45     816 1335.59   855.6  1359.6   895.2 1388.28   905.1 1397.63
#Mann= 3 , 0 , 0
       0      .1       0   481.2    .045       0   501.2      .1       0
Bank Sta=481.2,501.2
XS Rating Curve= 0 ,0
Exp/Cntr=0.3,0.1

Type RM Length L Ch R = 1 ,2263.6  ,211.7,214.1,216.5
XS GIS Cut Line= 4
      1684654.61      223545.008      1684615.93      223159.548
     1684559.912      222996.829     1684306.496      222794.096
#Sta/Elev= 30
     9.9 1414.22    49.7 1390.41    59.6 1385.71    69.5 1384.87   158.9 1331.66
   168.9  1331.4   178.8 1326.05   258.3 1278.72   288.1 1268.17   317.9 1251.56
   327.8  1245.3   337.7 1234.02   347.7 1217.42   357.6 1204.65   367.5 1201.13
   427.9  1204.8   478.6  1195.2   488.6 1195.12   498.6 1195.69   549.4 1202.58
   569.3 1207.48   618.5 1234.68   628.3 1236.76   638.2 1240.93   667.7 1260.79
   746.3 1308.28   775.8 1328.24   805.3 1344.98   834.8 1354.31     884  1383.7
#Mann= 3 , 0 , 0
       0      .1       0   478.6    .045       0   498.6      .1       0
Bank Sta=478.6,498.6
XS Rating Curve= 0 ,0
Exp/Cntr=0.3,0.1

Type RM Length L Ch R = 1 ,2049.5  ,203.8,201.1,198.4
XS GIS Cut Line= 4
     1684858.676      223479.653     1684809.327      223102.196
     1684755.976      222875.456     1684629.268      222695.397
#Sta/Elev= 30
      10 1342.22    30.1 1339.02    50.1 1337.51    90.2 1331.04   180.3 1306.43
   200.4 1303.06   250.4 1287.46   260.5 1283.35   290.5 1265.07   300.5  1263.5
   310.5 1258.77   340.6 1239.55   350.6 1227.73   360.6    1211   370.7 1199.02
   380.7    1197   411.1 1198.84   431.3 1198.57   471.9 1191.43   481.9 1190.95
   491.9 1191.44   583.2 1197.83   593.3 1199.19   623.6 1208.44   673.6 1240.95
   743.7  1292.2   753.7 1294.06   763.7 1299.84   803.8 1334.06   833.8 1355.18
#Mann= 3 , 0 , 0
       0     .08       0   471.9    .045       0   491.9     .08       0
Bank Sta=471.9,491.9
XS Rating Curve= 0 ,0
Exp/Cntr=0.3,0.1

Type RM Length L Ch R = 1 ,1848.4  ,197.5,201,204.4
XS GIS Cut Line= 4
     1685138.767      223344.942       1685033.4      223099.529
     1684926.698      222798.097     1684730.634      222626.041
#Sta/Elev= 30
     9.9 1392.52    19.8 1386.18    29.7 1385.12    39.6 1380.35   128.6  1318.4
   148.4 1312.33   158.3 1305.81   207.7 1271.38   247.3  1238.4   267.1 1230.76
     307 1195.54     317  1191.4     347 1195.44     387 1195.15   426.9 1188.83
   436.9 1187.22   446.9 1187.29   546.9 1197.26   596.9 1210.95   616.9  1213.7
     627 1218.24     637 1225.49     647 1235.08   657.1 1241.94   677.1 1252.39
   697.2 1269.21   767.4 1310.84   787.5 1318.49   807.6 1333.79   847.7 1356.15
#Mann= 3 , 0 , 0
       0     .08       0   426.9    .045       0   446.9     .08       0
Bank Sta=426.9,446.9
XS Rating Curve= 0 ,0
Exp/Cntr=0.3,0.1

Type RM Length L Ch R = 1 ,1647.5  ,135.8,133.8,131.9
XS GIS Cut Line= 4
     1685261.474       223298.26     1685190.785       223000.83
     1685150.772      222807.434     1685164.109      222520.673
#Sta/Elev= 30
     9.9 1372.97    59.2 1339.44      69 1334.91    78.9 1333.01   167.7 1269.35
   177.5 1267.55   187.4 1262.33   256.4 1210.32   276.1 1191.99     286 1186.81
   325.5 1189.78   335.3 1189.56   394.6  1186.8   404.5 1185.94   424.1  1182.3
   434.1 1181.14   444.1 1181.47   483.5 1188.21     523 1192.09   532.9 1194.42
   572.5  1213.7   602.2 1229.76   612.1 1230.47     622 1235.21   661.6 1259.04
   681.4 1272.42   701.2 1287.47   711.1 1290.65     721 1295.55   790.3  1353.2
#Mann= 3 , 0 , 0
       0     .08       0   424.1    .045       0   444.1     .08       0
Bank Sta=424.1,444.1
XS Rating Curve= 0 ,0
Exp/Cntr=0.3,0.1

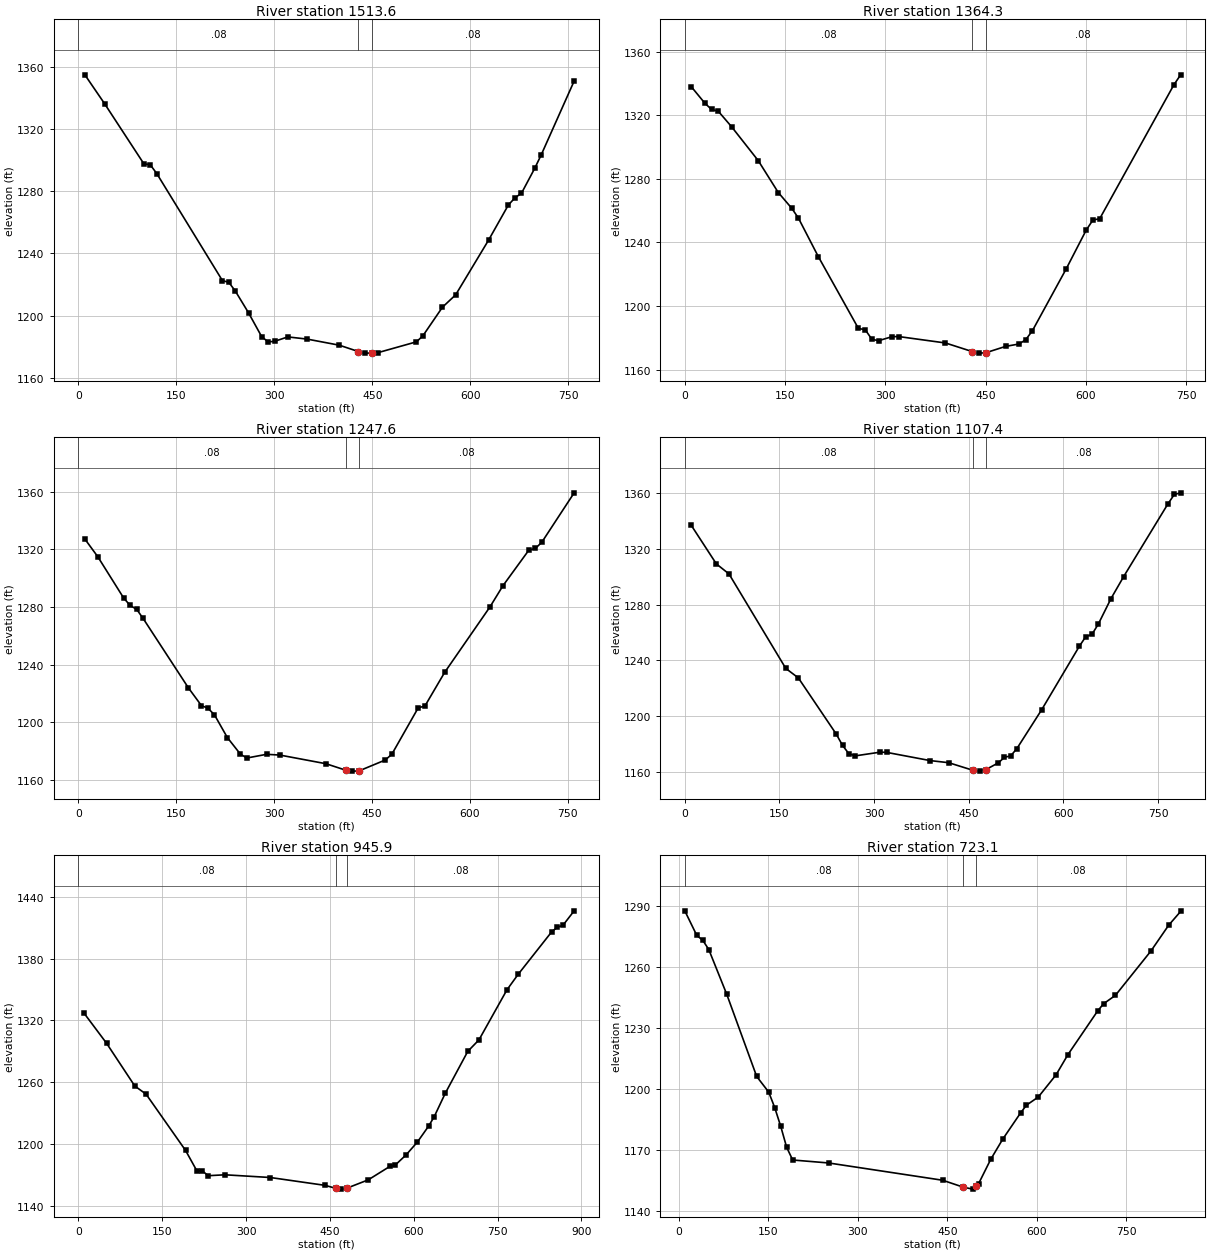
Type RM Length L Ch R = 1 ,1513.6  ,150.6,149.3,148.1
XS GIS Cut Line= 4
     1685448.202      223246.243     1685325.495      222950.147
     1685265.476      222742.079       1685238.8      222522.007
#Sta/Elev= 30
      10 1354.99    40.1 1336.46   100.2 1297.76   110.2 1297.03   120.2 1291.31
   220.4 1222.58   230.4 1221.36   240.4 1215.68   260.4 1201.82   280.5 1186.48
   290.5 1183.04   300.5 1183.46   320.5 1186.28     350 1184.88   399.3 1180.95
   428.6 1176.85   438.6 1175.84   448.6 1175.86   458.3 1176.13   517.4 1183.12
   527.2 1186.97   557.2 1205.42   577.4 1213.38   627.8 1248.63     658 1271.18
   668.1 1275.82   678.1 1278.77   698.3 1294.76   708.4 1303.57   758.7 1351.01
#Mann= 3 , 0 , 0
       0     .08       0   428.6    .045       0   448.6     .08       0
Bank Sta=428.6,448.6
XS Rating Curve= 0 ,0
Exp/Cntr=0.3,0.1

Type RM Length L Ch R = 1 ,1364.3  ,116.7,116.7,116.7
XS GIS Cut Line= 4
     1685561.572      223199.562     1685496.218      222968.819
     1685398.852      222684.727     1685293.485      222512.671
#Sta/Elev= 30
      10 1337.81      30 1327.59      40 1323.66      50 1322.58    69.9 1312.83
   109.9 1291.45   139.9 1271.38   159.9 1261.55   169.9  1255.4   199.8 1231.06
   259.8 1185.87   269.9 1185.13   279.9  1179.1   289.9 1178.18   309.9  1180.7
   319.9  1180.8     390 1176.76     430 1171.36     440 1170.37     450 1170.55
   480.1 1174.62   500.1 1176.11   510.1 1178.78   520.1 1184.46   570.4 1223.14
   600.7 1247.82   610.7 1254.12   620.8  1254.9   731.8 1339.15   741.9 1345.43
#Mann= 3 , 0 , 0
       0     .08       0     430    .045       0     450     .08       0
Bank Sta=430,450
XS Rating Curve= 0 ,0
Exp/Cntr=0.3,0.1

Type RM Length L Ch R = 1 ,1247.6  ,139.8,140.2,140.6
XS GIS Cut Line= 4
      1685656.27      223146.211     1685590.915      222886.126
     1685496.218      222608.702     1685346.835      222477.993
#Sta/Elev= 30
     9.9  1327.3    29.8 1314.97    69.5 1286.26    79.5 1281.09    89.4 1278.42
    99.3 1272.09   168.8 1223.82   188.7 1211.55   198.6  1209.8   208.6 1205.17
   228.4 1189.36   248.3 1177.91   258.2 1175.19   288.4 1177.76   308.6 1177.26
   379.4 1171.24   409.8 1166.74   419.8 1166.09   429.8 1166.18   470.3  1173.8
   480.4  1177.8   520.9  1210.1     531 1211.21   561.3 1234.62   630.8 1280.12
   650.6 1294.77   690.3 1319.48   700.3 1320.68   710.2    1325   759.8 1359.32
#Mann= 3 , 0 , 0
       0     .08       0   409.8    .045       0   429.8     .08       0
Bank Sta=409.8,429.8
XS Rating Curve= 0 ,0
Exp/Cntr=0.3,0.1

Type RM Length L Ch R = 1 ,1107.4  ,163.2,161.5,159.7
XS GIS Cut Line= 4
     1685837.662      223132.873     1685716.289      222826.106
     1685637.597       222583.36      1685514.89      222424.642
#Sta/Elev= 30
      10 1336.82      50 1309.07      70 1301.89     160  1234.3   179.9  1227.5
   239.9 1187.35   249.9 1179.25   259.9 1173.29   269.9  1171.7   309.9 1174.38
   319.9  1174.2   388.8 1168.33   418.2 1166.82   457.3 1161.29   467.3 1160.79
   477.3 1161.94   496.8 1166.71   506.6 1170.69   516.4  1171.7   526.2  1176.9
   565.5  1204.7   625.2 1250.13   635.2 1256.88   645.3 1258.71   655.3 1266.02
   675.4 1284.29   695.4 1299.96   765.6 1352.02   775.7 1358.73   785.7 1359.91
#Mann= 3 , 0 , 0
       0     .08       0   457.3    .045       0   477.3     .08       0
Bank Sta=457.3,477.3
XS Rating Curve= 0 ,0
Exp/Cntr=0.3,0.1

Type RM Length L Ch R = 1 ,945.9   ,224,222.8,221.7
XS GIS Cut Line= 4
     1685957.701      223094.194     1685859.003      222723.406
     1685786.979      222544.681     1685576.244      222316.607
#Sta/Elev= 30
    10.1 1327.16    50.5 1297.84     101 1256.33   121.2 1248.39   191.8 1193.77
     212 1173.96   222.1 1173.79   232.2 1169.22   262.5  1170.1   343.3 1167.47
   441.5 1159.83   460.4 1156.98   470.4 1156.18   480.4 1157.11   518.6  1165.2
   557.1 1178.21   566.8  1179.5   586.4  1189.5   606.4 1201.85   626.5 1217.32
   636.5 1226.45   656.5 1249.44   696.6 1289.96   716.6 1301.13   766.7 1349.75
   786.7 1364.77   846.9  1406.2   856.9 1410.52   866.9 1412.44   886.9 1426.46
#Mann= 3 , 0 , 0
       0     .08       0   460.4    .045       0   480.4     .08       0
Bank Sta=460.4,480.4
XS Rating Curve= 0 ,0
Exp/Cntr=0.3,0.1

Type RM Length L Ch R = 1 ,723.1   ,221.3,216.7,212.1
XS GIS Cut Line= 4
     1686135.093      223044.844     1686107.083       222724.74
     1686015.053      222523.341     1685867.005       222264.59
#Sta/Elev= 30
      10 1287.55    30.1 1275.45    40.2 1273.02    50.2 1268.51    80.3 1246.49
   130.5 1206.05   150.6 1198.39   160.7 1190.74   170.7 1181.59   180.7 1171.21
   190.8 1164.97     251 1163.51   442.1 1155.01  476.51 1151.62   492.4 1150.64
   497.5 1152.02   502.5  1153.4   522.6 1165.25   542.8 1175.23   572.6 1188.08
   582.5 1191.93   602.4 1195.96   632.2 1206.89   652.1 1216.84   701.7 1238.23
   711.7 1241.83   731.6 1245.96   791.2 1267.81     821 1280.52   840.9 1287.25
#Mann= 3 , 0 , 0
      10     .08       0  476.51    .045       0   497.5     .08       0
Bank Sta=476.51,497.5
XS Rating Curve= 0 ,0
Exp/Cntr=0.3,0.1

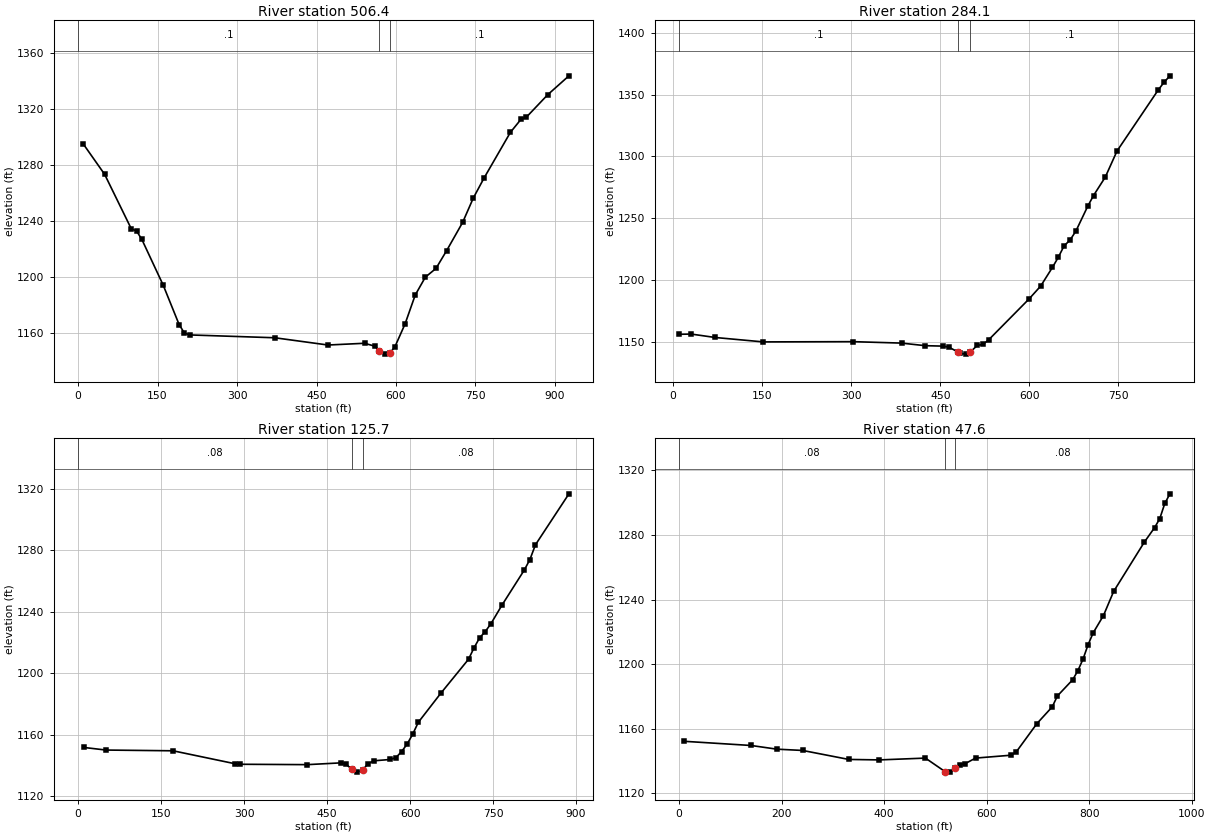
Type RM Length L Ch R = 1 ,506.4   ,218.8,222.2,225.7
XS GIS Cut Line= 4
     1686285.809       223022.17     1686253.798      222511.337
     1686171.104      222393.965     1685961.703      222221.909
#Sta/Elev= 30
      10 1294.77    50.2 1273.11   100.4 1234.23   110.4 1232.65   120.4 1226.59
   160.6 1193.97   190.7 1165.75   200.7 1159.66   210.8 1158.35   371.3 1156.32
   471.7 1151.13   540.6 1152.38   559.7 1150.34   568.8 1147.15   578.8 1144.62
   588.8 1145.51     598 1149.91   617.1 1166.19   636.3 1186.87   655.4 1199.65
   675.5  1205.9   695.6 1218.64   725.7 1238.74   745.8 1256.13   765.8 1270.27
     816 1303.23   836.1  1312.6   846.1 1314.05   886.3 1330.07   926.4  1343.6
#Mann= 3 , 0 , 0
       0      .1       0   568.8    .045       0   588.8      .1       0
Bank Sta=568.8,588.8
XS Rating Curve= 0 ,0
Exp/Cntr=0.3,0.1

Type RM Length L Ch R = 1 ,284.1   ,149.9,158.4,162.3
XS GIS Cut Line= 5
     1686336.403      222800.383     1686359.041      222416.381
     1686409.625      222354.555     1686361.851      222261.115
     1686165.914      222079.503
#Sta/Elev= 30
    10.1 1156.08    30.4 1156.26    70.9 1153.48   151.8 1149.91   303.7  1150.1
   384.7 1148.94   424.6 1146.85   454.6  1146.5   464.6 1145.61   480.6 1141.54
   483.6 1140.61   493.2 1140.02  500.11 1141.58   512.3 1147.07   521.8 1147.87
   531.3 1151.52   599.2 1184.53     619 1195.06   638.8 1210.15   648.7 1218.36
   658.5 1227.63   668.4 1232.24   678.3 1239.52   698.1 1259.49     708  1268.3
   727.8 1283.19   747.6 1304.34   816.9 1353.65   826.8 1359.97   836.7 1365.16
#Mann= 3 , 0 , 0
    10.1      .1       0   480.6    .045       0  500.11      .1       0
Bank Sta=480.6,500.11
XS Rating Curve= 0 ,0
Exp/Cntr=0.3,0.1

Type RM Length L Ch R = 1 ,125.7   ,78.2,78.1,67
XS GIS Cut Line= 4
     1686380.118      222734.758     1686542.786       222299.74
     1686534.791      222240.519     1686259.133      222004.505
#Sta/Elev= 30
    10.1 1151.76    50.5 1150.05   171.6 1149.57   282.7 1141.21   292.8  1140.8
     414 1140.55   474.4  1141.7   484.4  1140.9   494.3 1137.56   504.3 1135.68
   514.3 1137.15   524.2 1141.17   534.3 1143.05   564.5 1143.92   574.6  1145.2
   584.7 1149.09   594.8    1154   604.8 1160.43   614.9 1168.12   655.2 1186.87
   705.6 1209.15   715.7  1216.7   725.8 1223.17   735.9 1227.22     746 1232.22
   766.1 1244.42   806.4 1267.24   816.5 1274.03   826.6  1283.7   887.1 1316.86
#Mann= 3 , 0 , 0
       0     .08       0   494.3    .045       0   514.3     .08       0
Bank Sta=494.3,514.3
XS Rating Curve= 0 ,0
Exp/Cntr=0.3,0.1

Type RM Length L Ch R = 1 ,47.6    ,49.4,47.6,61.4
XS GIS Cut Line= 5
     1686426.018      222735.695     1686535.674       222465.89
     1686617.914      222273.458     1686612.667      222235.857
     1686288.316      221970.371
#Sta/Elev= 30
      10 1152.29   140.6  1149.7   190.8 1147.42     241 1146.63   331.1 1141.07
   390.9 1140.78   480.6  1141.9     519 1133.52     529 1133.22     539 1135.51
   548.5 1137.88   558.4 1138.52   578.4  1141.9   648.2  1143.7   658.2 1145.91
   698.1 1163.24   728.1 1173.65   738.1 1180.37     768 1190.41     778 1195.99
     788 1203.09   797.9 1212.02   807.9 1219.41   827.9 1230.07   847.8    1245
   907.7 1275.52   927.7 1284.49   937.7 1289.97   947.6 1299.46   957.6 1305.38
#Mann= 3 , 0 , 0
       0     .08       0     519    .045       0     539     .08       0
Bank Sta=519,539
XS Rating Curve= 0 ,0
Exp/Cntr=0.3,0.1

Chan Stop Cuts=-1
Use User Specified Reach Order=0